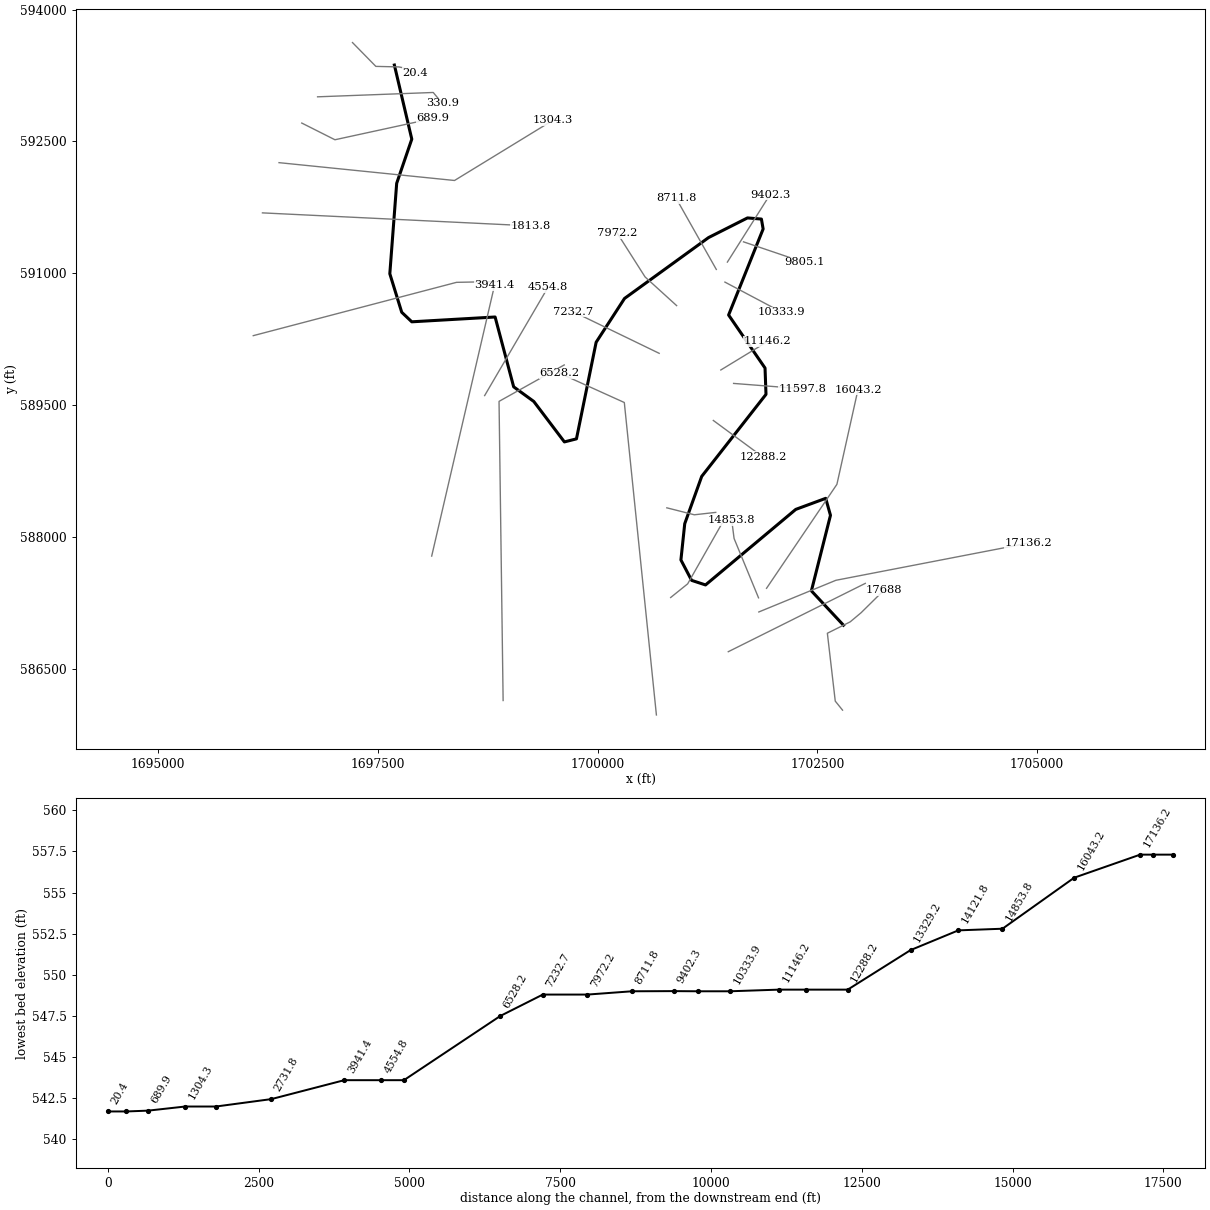
--- EightenmC8.prj (project) ---

Proj Title=EightenmC8
Current Plan=p01
Default Exp/Contr=0,0
English Units
Geom File=g01
Flow File=f01
Plan File=p01
BEGIN DESCRIPTION:
AMEC Environment & Infrastructure, 2013
Projection: NAD 1983 State Plane West Virginia South FIPS 4702 (US Feet)
Vertical Datum: NAVD 1988
END DESCRIPTION:
DSS Export Rating Curves= 0
DSS Export Rating Curve Sorted= 0
DSS Export Volume Flow Curves= 0
DXF OffsetX= 0
DXF OffsetY= 0
DXF ScaleX= 0
DXF ScaleY= 0

--- EightenmC8.p01 (plan) ---

Plan Title=Floodplain
Program Version=4.00
Geom File=g01
Flow File=f01
K Sum by GR=0
Std Step Tol=0.01
Critical Tol=0.01
Num of Std Step Trials=20
Max Error Tol=0.3
Flow Tol Ratio=0.001
Split Flow NTrial=30
Split Flow Tol=0.02
Split Flow Ratio=0.02
Log Output Level=0
Friction Slope Method=1
Unsteady Friction Slope Method=2
Unsteady Bridges Friction Slope Method=1
Global Log Level=0
CheckData=False
Run HTab=0
Run UNet=0
Run PostProcess=0
UNET Theta=0
UNET Theta Warmup=0
UNET ZTol=0
UNET ZSATol=0
UNET MxIter=0
UNET MaxInSteps=0
UNET DtIC=0
UNET DtMin=0
UNET MaxCRTS=0
UNET WFStab=0
UNET SFStab=0
UNET WFX=0
UNET SFX=0
UNET DSS MLevel=0
UNET DZMax Abort=0
UNET Convert EG Bridges=0
UNET Use Existing IB Tables=0
UNET Froude Limit=0
UNET Froude Power=0
Write IC File=0
Echo Input=False
Echo Output=False
Write Detailed=0

--- EightenmC8.f01 (steady flow) ---

Flow Title=USGS Regress. Eqn. (2010) - Western-Plateaus
Program Version=4.10
Number of Profiles= 1
Profile Names=P100yr
River Rch & RM=EightenmC8,Main            ,17688
    9700
River Rch & RM=EightenmC8,Main            ,14121.8
    9785
River Rch & RM=EightenmC8,Main            ,13329.2
    9791
River Rch & RM=EightenmC8,Main            ,7972.2
    9817
River Rch & RM=EightenmC8,Main            ,3941.4
    9958
River Rch & RM=EightenmC8,Main            ,20.4
   10069
Boundary for River Rch & Prof#=EightenmC8,Main            , 1
Up Type= 0
Dn Type= 1
Dn Known WS=571.98
DSS Import GetInterval= 0
DSS Import GetPeak= 0
DSS Import FillOption= 0

--- EightenmC8.g01 (geometry) ---

Geom Title=USGS 3m DEM
Program Version=4.10
BEGIN GEOM DESCRIPTION:
Compared to the upstream detailed studied stream to determine discrepancy of WS Elevations. It appears that the terrain variation is about 1-3 feet depending on station as well as the FIS study producing lesser Q100 flows.
END GEOM DESCRIPTION:

River Reach=EightenmC8      ,Main
Reach XY= 30
     1702796.901      586996.492     1702431.945      587387.329
     1702648.959      588246.704     1702594.706      588439.846
     1702253.994      588313.978     1701227.518      587454.603
     1701069.098      587506.686      1700947.57      587738.891
     1700990.973      588151.217     1701184.115      588689.412
     1701915.452      589622.572     1701904.602      589922.051
     1701490.105      590525.349       1701882.9      591504.082
     1701863.369      591616.929     1701704.949       591629.95
      1701262.24      591406.426     1700306.077      590713.717
     1699983.161      590215.454     1699759.202      589116.495
      1699622.05      589081.773     1699273.959      589541.842
     1699044.793      589708.509     1698833.855       590502.78
     1697885.938      590448.092     1697771.369       590556.66
     1697635.938      590994.967     1697714.063      592023.613
     1697885.938      592526.217     1697687.822      593369.168

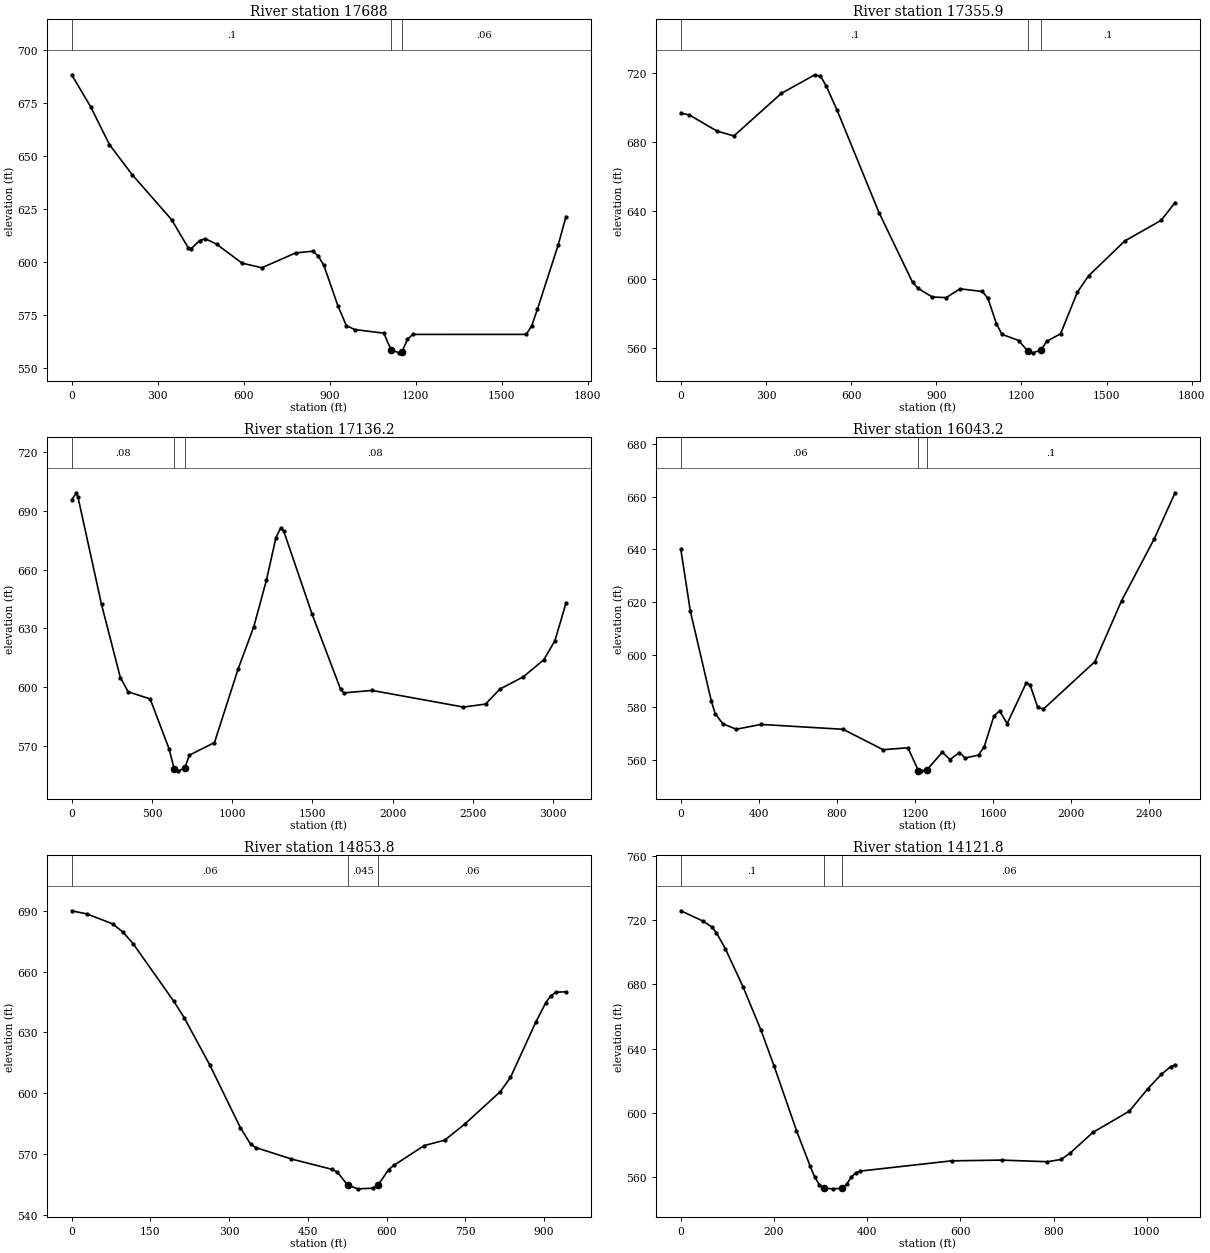
Type RM Length L Ch R = 1 ,17688   ,333.3,332.1,331.6
XS GIS Cut Line= 6
     1702786.272      586030.365     1702703.417      586132.885
     1702613.705      586905.093     1702873.126       587034.52
     1702998.297      587139.335     1703255.429      587393.119
#Sta/Elev= 30
       0  688.41    65.9  673.38   131.8  655.47   210.5  641.38   348.2  620.13
   407.2  606.69   417.1  606.49   446.6  610.25   466.3   611.1   505.6  608.51
   594.2  599.59     663  597.42   781.1  604.41   840.1  605.22   859.8  602.96
   879.4  598.55   928.6  579.39   957.8  570.15   986.5   568.3  1088.6  566.56
    1114  558.65  1142.5   557.3    1152  557.84  1170.9   563.7  1189.7  565.99
  1584.8     566  1604.2  569.98  1624.3   577.9  1696.6  608.16  1723.7  621.51
#Mann= 3 , 0 , 0
       0      .1       0    1114    .045       0    1152     .06       0
Bank Sta=1114,1152
XS Rating Curve= 0 ,0
Exp/Cntr=0.3,0.1

Type RM Length L Ch R = 1 ,17355.9 ,220.2,219.7,218.6
XS GIS Cut Line= 2
     1701486.519      586695.096     1703045.029      587472.365
#Sta/Elev= 30
       0  696.74    29.5   695.8   127.9  686.34     187  683.53   354.2   708.3
   472.3  719.13     492  718.33   511.6  712.89     551   698.4   698.6  638.84
   816.7  598.31   836.4   594.8   885.6  589.83   934.8  589.42   983.9  594.56
  1062.7     593  1082.3  588.95  1111.9  574.34  1131.5  568.08  1190.6  564.48
  1223.5   558.1  1239.8   557.3  1269.3  558.93    1289  563.98  1338.2   568.4
  1397.2  592.56  1436.6  602.07  1564.5  622.43  1692.4  634.39  1741.6  644.78
#Mann= 3 , 0 , 0
       0      .1       0  1223.5    .045       0  1269.3      .1       0
Bank Sta=1223.5,1269.3
XS Rating Curve= 0 ,0
Exp/Cntr=0.3,0.1

Type RM Length L Ch R = 1 ,17136.2 ,1079.5,1093,1106.4
XS GIS Cut Line= 3
     1701833.792      587147.087     1702710.733      587507.512
     1704895.411      587929.541
#Sta/Elev= 30
       0  695.66    29.3  699.25    39.1  697.06   185.7  642.28     303  604.94
   351.9  597.63   488.7  594.02     606  568.67   639.2  558.16   664.7   557.3
   703.8  558.63   733.1  565.31   889.5  571.72  1036.5  609.23  1134.7  630.95
  1213.3  654.67  1272.2  676.33  1301.6  681.26  1321.3   679.6    1498  637.22
  1674.8  599.01  1694.4  597.08  1871.2  598.35  2440.8  589.86  2578.2  591.38
  2666.6  598.98  2813.9  605.33  2941.6  614.05  3010.3  623.75  3079.1  642.86
#Mann= 3 , 0 , 0
       0     .08       0   639.2    .045       0   703.8     .08       0
Bank Sta=639.2,703.8
XS Rating Curve= 0 ,0
Exp/Cntr=0.3,0.1

Type RM Length L Ch R = 1 ,16043.2 ,1166.7,1189.4,1212
XS GIS Cut Line= 3
     1701921.693      587416.413     1702722.215      588599.149
      1702962.33      589677.821
#Sta/Elev= 30
       0  640.02    48.9  616.51   156.5  582.38   176.1  577.59   215.2   573.8
   283.7  571.69   410.8  573.52   831.5  571.67  1036.9  563.93  1164.1  564.66
  1217.2  556.02  1232.2   555.9  1261.9   556.3  1340.1  562.99  1379.3   560.2
  1428.2  562.85  1457.5  560.78    1526  561.89  1555.3   565.1  1604.2   576.6
  1633.6  578.68  1672.7  573.85  1770.5   589.3    1790  588.55  1829.1  580.06
  1858.5  579.34  2122.5  597.37  2259.4  620.52  2425.7  643.88  2533.2  661.46
#Mann= 3 , 0 , 0
       0     .06       0  1217.2    .045       0  1261.9      .1       0
Bank Sta=1217.2,1261.9
XS Rating Curve= 0 ,0
Exp/Cntr=0.3,0.1

Type RM Length L Ch R = 1 ,14853.8 ,752,732,712
XS GIS Cut Line= 3
     1701830.574      587307.976     1701552.392      587983.087
     1701525.449      588192.903
#Sta/Elev= 30
       0     690    29.2  688.43    77.9  683.56    97.4  679.55   116.8  673.85
   194.7  645.28   214.2   637.3   262.9  614.02   321.3  583.01   340.8  574.87
   350.5  573.18   418.6  567.52   496.5  562.39   506.3  561.04   525.7  554.67
   545.2   552.8   574.4  553.12   584.1   554.8   603.6  562.26   613.4  564.32
   671.8  574.18   710.7  576.81   749.4  584.87   816.7  600.78     836  607.77
     884  634.93   903.3  644.68   912.9  648.04   922.5  649.79   941.7  650.06
#Mann= 3 , 0 , 0
       0     .06       0   525.7    .045       0   584.1     .06       0
Bank Sta=525.7,584.1
XS Rating Curve= 0 ,0
Exp/Cntr=0.3,0.1

Type RM Length L Ch R = 1 ,14121.8 ,822.9,792.6,762.3
XS GIS Cut Line= 3
       1700830.9      587311.521      1701024.27      587467.083
     1701425.492      588173.289
#Sta/Elev= 30
       0  725.74    47.7   719.3    66.8  715.64    76.4  712.05    95.4  702.24
   133.6  678.38   171.8   651.6   200.4  628.94   248.2  588.93   277.5  566.84
   287.3     560   297.1  555.32   306.4  553.14   326.5   552.7     346  553.03
   355.8  555.56   365.6  559.93   375.4  562.74   385.2  563.76   580.9  570.13
   688.5  570.58   786.4  569.57   815.8  570.99   835.3  574.96   884.2  587.85
   962.5  601.09  1001.7  614.93    1031  623.98  1050.6  628.66  1060.4  629.99
#Mann= 3 , 0 , 0
       0      .1       0   306.4    .045       0     346     .06       0
Bank Sta=306.4,346
XS Rating Curve= 0 ,0
Exp/Cntr=0.3,0.1

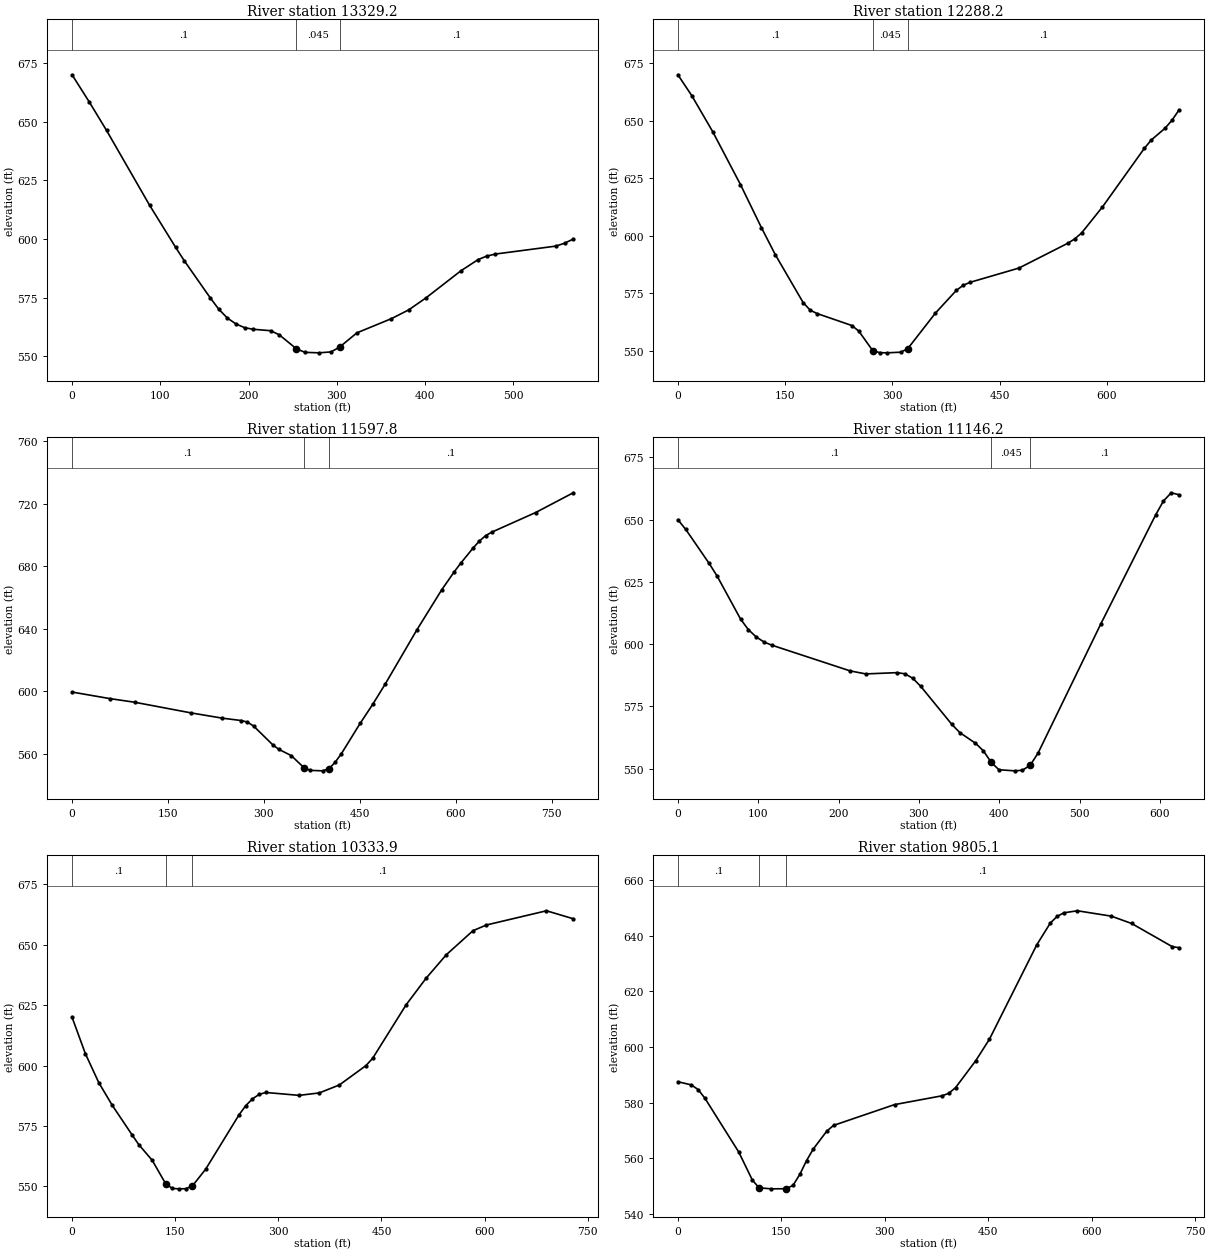
Type RM Length L Ch R = 1 ,13329.2 ,1050.1,1041,1031.8
XS GIS Cut Line= 3
     1700787.269      588331.937     1701100.062      588252.656
     1701343.631      588280.017
#Sta/Elev= 30
       0     670    19.6  658.37    39.1  646.28      88  614.31   117.3  596.49
   127.1  590.77   156.4  575.03   166.2   570.1     176  566.32   185.8  563.79
   195.6  562.21   205.3  561.54   224.9  560.94   234.7  559.21   254.2   553.2
     264  551.71   279.7   551.5   293.4   551.9   303.1  553.94   322.7  560.02
   361.9  566.08   381.5  569.83   401.1  574.96   440.3   586.4   459.9  591.21
   469.7  592.72   479.6   593.6   548.2  596.99     558  598.22   567.8     600
#Mann= 3 , 0 , 0
       0      .1       0   254.2    .045       0   303.1      .1       0
Bank Sta=254.2,303.1
XS Rating Curve= 0 ,0
Exp/Cntr=0.3,0.1

Type RM Length L Ch R = 1 ,12288.2 ,677.7,690.5,703.2
XS GIS Cut Line= 2
      1701316.24      589325.846     1701880.687      588910.195
#Sta/Elev= 30
       0  670.01    19.5  660.92    48.7  645.29    87.6  622.25   116.8  603.59
   136.3  591.77   175.2  570.97     185  567.67   194.7  566.19   243.4  560.97
   253.1  558.54   272.6  550.04   282.3  549.19   292.1   549.1   311.5  549.38
   321.3  550.83   360.2  566.37   389.4  576.23   399.2   578.5   408.9  579.78
     477  585.96   545.2  596.72   554.9  598.61   564.7  601.23   593.9  612.56
   652.3  637.96     662  641.61   681.5   646.8   691.2  650.28     701  654.73
#Mann= 3 , 0 , 0
       0      .1       0   272.6    .045       0   321.3      .1       0
Bank Sta=272.6,321.3
XS Rating Curve= 0 ,0
Exp/Cntr=0.3,0.1

Type RM Length L Ch R = 1 ,11597.8 ,437.3,451.5,465.8
XS GIS Cut Line= 2
     1701547.007      589747.148     1702328.476      589686.443
#Sta/Elev= 30
       0  599.48    58.8  595.31      98  592.96   186.2  586.14   235.2  582.77
   264.5  581.27   274.3  580.28   284.1  577.68   313.5  565.91   323.3  562.86
   342.9  558.83   362.5  551.18   372.3  549.41   391.9   549.1   401.7  550.42
   411.5   554.6   421.3  560.12   450.7  579.55   470.3  591.67   489.9  604.69
   538.9  638.99   578.1  664.86   597.7  676.38   607.5   681.7   627.1  691.52
   636.9  695.97   646.6  699.44   656.4  701.73     725  714.27   783.8   726.9
#Mann= 3 , 0 , 0
       0      .1       0   362.5    .045       0   401.7      .1       0
Bank Sta=362.5,401.7
XS Rating Curve= 0 ,0
Exp/Cntr=0.3,0.1

Type RM Length L Ch R = 1 ,11146.2 ,835.8,812.4,788.9
XS GIS Cut Line= 2
     1701401.516      589900.018     1701934.364      590224.355
#Sta/Elev= 30
       0     650     9.8   646.1      39   632.4    48.7  627.43      78   610.1
    87.7  605.84    97.5  602.91   107.2  600.86     117  599.58   214.4  589.25
   233.9  588.04   272.9  588.55   282.7  588.08   292.4  586.27   302.2  583.08
   341.1  567.72   350.9  564.47   370.4  560.19   380.1   557.2   389.9  552.56
   399.6  549.54   419.1   549.1   428.9  549.34   438.6  551.37   448.4   556.3
   526.3  608.06   594.6   651.9   604.3  657.47     614  660.81   623.8  660.02
#Mann= 3 , 0 , 0
       0      .1       0   389.9    .045       0   438.6      .1       0
Bank Sta=389.9,438.6
XS Rating Curve= 0 ,0
Exp/Cntr=0.3,0.1

Type RM Length L Ch R = 1 ,10333.9 ,525.2,528.8,532.4
XS GIS Cut Line= 2
     1701448.353      590899.759     1702092.456      590558.519
#Sta/Elev= 30
       0  619.99    19.4   604.9    38.9  592.92    58.3  583.63    87.5  571.24
    97.2  567.24   116.6   560.8   136.1  551.14   145.8  549.18   155.5     549
   165.2  549.04   174.9  550.15   194.4  557.16     243  579.68   252.7  583.42
   262.4  586.22   272.1  588.05   281.8  588.86   330.4  587.66   359.6  588.68
   388.8  591.97   427.6  600.01   437.4  603.09   485.9  625.14   515.1  636.18
   544.2   645.8   583.1  655.77   602.6  658.13     690  664.01   728.9  660.71
#Mann= 3 , 0 , 0
       0      .1       0   136.1    .045       0   174.9      .1       0
Bank Sta=136.1,174.9
XS Rating Curve= 0 ,0
Exp/Cntr=0.3,0.1

Type RM Length L Ch R = 1 ,9805.1  ,372.9,402.8,432.7
XS GIS Cut Line= 2
     1701659.728      591357.841     1702348.022      591124.562
#Sta/Elev= 30
       0  587.53    19.6  586.38    29.5  584.68    39.3  581.56    88.4  562.19
     108  552.16   117.8  549.36   135.7     549   157.1  549.04     167  550.25
   176.8  554.17   186.6  559.16   196.4  563.34   216.1  569.81   225.9  571.83
   314.3   579.3     383  582.46   392.8  583.34   402.7   585.4   432.1  595.14
   451.8  602.81   520.5  636.78   540.2  644.64     550  646.98   559.8  648.28
   579.4  649.01   628.5  647.08     658  644.44   716.9  636.11   726.8  635.73
#Mann= 3 , 0 , 0
       0      .1       0   117.8    .045       0   157.1      .1       0
Bank Sta=117.8,157.1
XS Rating Curve= 0 ,0
Exp/Cntr=0.3,0.1

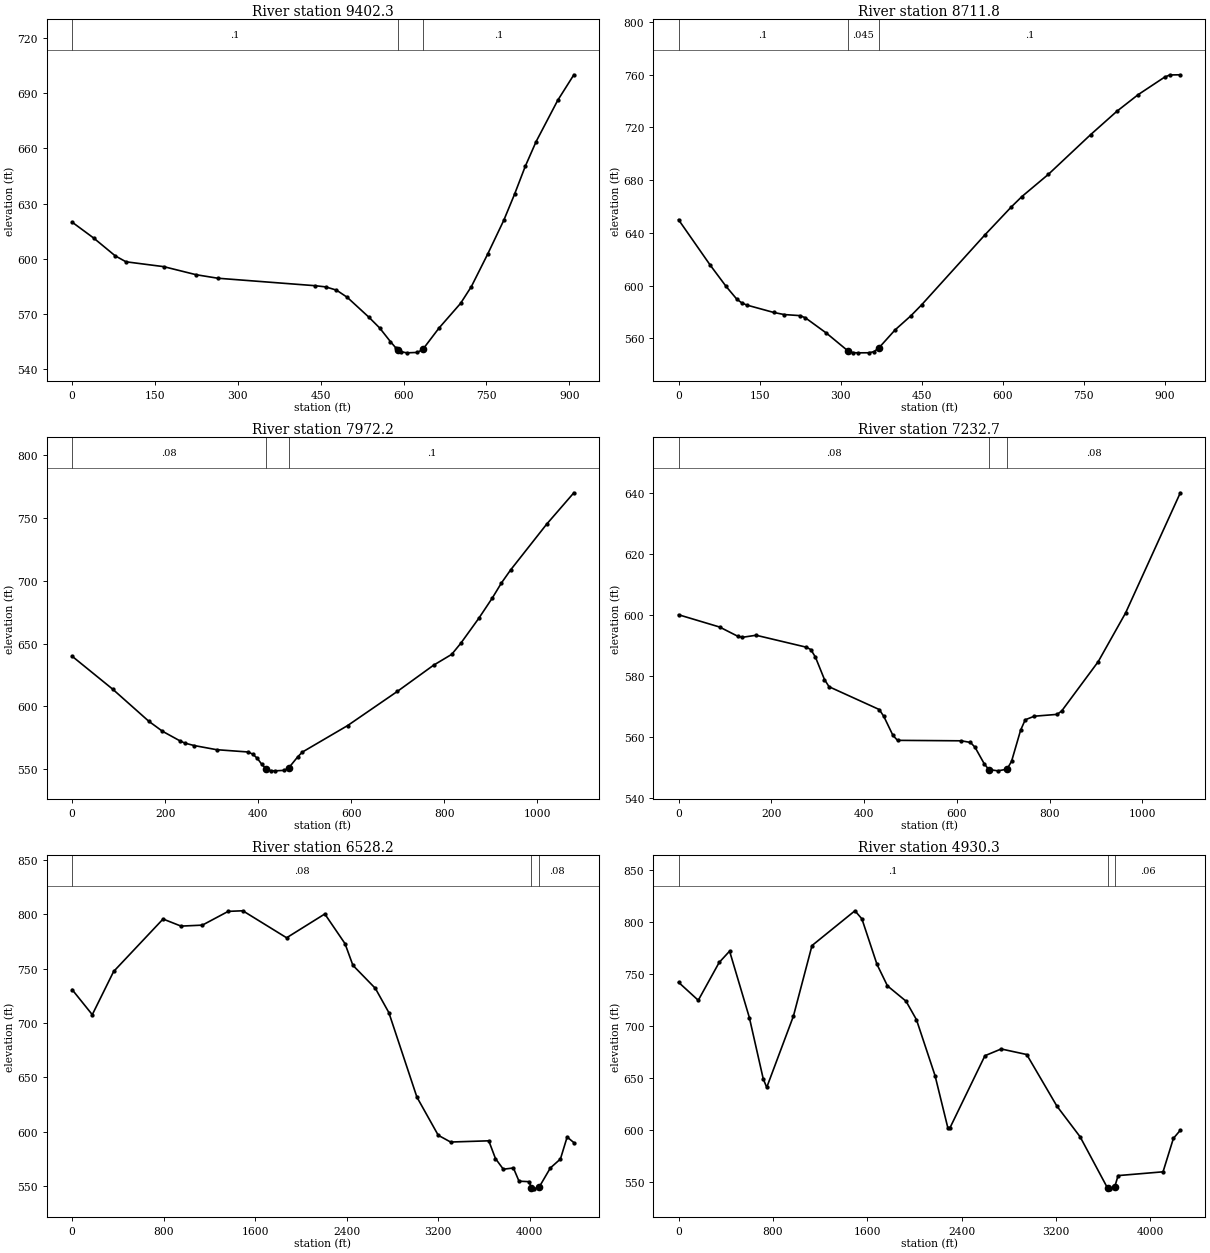
Type RM Length L Ch R = 1 ,9402.3  ,664.9,690.5,716.1
XS GIS Cut Line= 2
     1701476.244      591127.579     1701961.489      591895.177
#Sta/Elev= 30
       0     620    39.1  611.35    78.1  601.68    97.6  598.45     166  595.81
   224.6  591.43   263.6  589.53   439.4  585.48   458.9  584.83   478.5  583.07
     498  579.16   537.1  568.38   556.6  562.54   576.1  555.12   585.9  551.71
   590.5  550.73   595.6  549.64   605.4  549.01   624.9  549.23   634.7  550.86
     664  562.45   703.1  575.88   722.6  584.99   751.9  602.49   781.2  620.94
   800.7  635.09   820.2  650.33   839.8  663.73   878.8  686.09   908.1  700.01
#Mann= 3 , 0 , 0
       0      .1       0   590.5    .045       0   634.7      .1       0
Bank Sta=590.5,634.7
XS Rating Curve= 0 ,0
Exp/Cntr=0.3,0.1

Type RM Length L Ch R = 1 ,8711.8  ,732.3,739.6,746.8
XS GIS Cut Line= 2
      1701350.18      591043.871     1700893.239      591852.845
#Sta/Elev= 30
       0  650.02    58.7  615.53      88  599.44   107.6  589.87   117.4  586.77
   127.1  585.17     176  579.67   195.6  578.05   224.9  577.24   234.7  575.63
   273.8  563.97     313   550.7   322.7  549.16   332.5     549   352.1  549.05
   361.9  549.88   371.6  553.05     401  566.42   430.3  577.15   449.9  585.34
   567.2  638.48   616.1  659.69   635.7  667.57   684.6  684.39   762.8  714.49
   811.7  732.33   850.9  744.88   899.8  758.16   909.5  759.86   929.1     760
#Mann= 3 , 0 , 0
       0      .1       0     313    .045       0   371.6      .1       0
Bank Sta=313,371.6
XS Rating Curve= 0 ,0
Exp/Cntr=0.3,0.1

Type RM Length L Ch R = 1 ,7972.2  ,733.2,739.5,746
XS GIS Cut Line= 3
     1700898.747      590632.375     1700539.687      590958.696
     1700221.404      591459.145
#Sta/Elev= 30
       0     640    87.3  613.76     165  588.21   194.1  580.32   232.9  572.44
   242.6  570.84     262  568.95   310.5  565.63   378.4  563.79   388.2  562.07
   397.9  558.83   407.6  554.03   417.3  550.23     427  548.89   436.7   548.8
   456.1  549.19   465.8  551.26   485.2  560.05   494.9  563.73   592.1   584.8
   699.1  612.01   776.9  632.85   815.8  641.46   835.2  650.22   874.1  670.19
   903.3  686.44   922.7  698.28   942.2  708.53  1019.9  745.05  1078.3     770
#Mann= 3 , 0 , 0
       0     .08       0   417.3    .045       0   465.8      .1       0
Bank Sta=417.3,465.8
XS Rating Curve= 0 ,0
Exp/Cntr=0.3,0.1

Type RM Length L Ch R = 1 ,7232.7  ,704,704.5,705
XS GIS Cut Line= 2
     1700700.149      590089.575     1699726.736       590561.02
#Sta/Elev= 30
       0     600    88.5  595.97   127.8  592.93   137.6   592.6   167.2  593.27
   275.3  589.36   285.1  588.57     295  586.12   314.6  578.74   324.5  576.38
   432.6  568.91   442.5  566.65   462.1  560.44     472   558.8   609.6  558.65
   629.3  558.11   639.1  556.52   658.8  551.15   668.6  549.23   688.3   548.8
   707.9  549.34   717.8  551.91   737.4  562.16   747.3  565.55   766.9  566.72
   816.1  567.32   825.9  568.44   904.6  584.61   963.6  600.58  1081.6     640
#Mann= 3 , 0 , 0
       0     .08       0   668.6    .045       0   707.9     .08       0
Bank Sta=668.6,707.9
XS Rating Curve= 0 ,0
Exp/Cntr=0.3,0.1

Type RM Length L Ch R = 1 ,6528.2  ,1650.7,1597.8,1544.5
XS GIS Cut Line= 3
     1700668.722      585975.467     1700303.639      589530.015
     1699563.738       589864.66
#Sta/Elev= 30
       0  730.76   176.7  707.64   363.2  747.34   795.2  795.59   952.2  789.07
  1138.7  789.97  1364.5  802.63  1492.1  803.17    1875  778.34  2208.7  800.24
  2385.4  772.95  2454.2  753.04  2650.5  731.83  2768.3  709.58  3013.7  631.82
  3200.2  596.74  3308.2  590.54  3641.7  591.66  3700.4   575.3  3768.9  565.54
    3857  566.69  3905.9  554.55    3994  554.08  4013.5   548.7  4033.1   547.5
    4082   549.1  4179.8  566.68  4267.9  574.93  4326.6  595.14  4385.3     590
#Mann= 3 , 0 , 0
       0     .08       0  4013.5    .045       0    4082     .08       0
Bank Sta=4013.5,4082
XS Rating Curve= 0 ,0
Exp/Cntr=0.3,0.1

Type RM Length L Ch R = 1 ,4930.3  ,352.1,375.6,400.6
XS GIS Cut Line= 3
     1698925.011      586139.629     1698878.536       589542.91
     1699620.065      589957.296
#Sta/Elev= 30
       0  742.32   167.2  724.98   344.3  761.37   432.8  772.27   600.1  708.43
   718.1  649.31   747.6   641.2   973.9  709.82  1131.2  777.63  1495.2   811.1
  1554.2  803.31  1682.1  759.54  1770.7  738.86    1928  724.16  2016.6  706.34
    2174  652.56  2282.2  602.48  2301.9  602.59    2597  671.67  2734.7  678.15
  2951.1  672.82  3206.9  623.19  3403.6  593.68  3637.9  543.99  3652.9   543.6
  3696.5  545.35  3725.8  556.34  4106.6  559.98  4194.5  592.16  4253.1     600
#Mann= 3 , 0 , 0
       0      .1       0  3637.9    .045       0  3696.5     .06       0
Bank Sta=3637.9,3696.5
XS Rating Curve= 0 ,0
Exp/Cntr=0.3,0.1

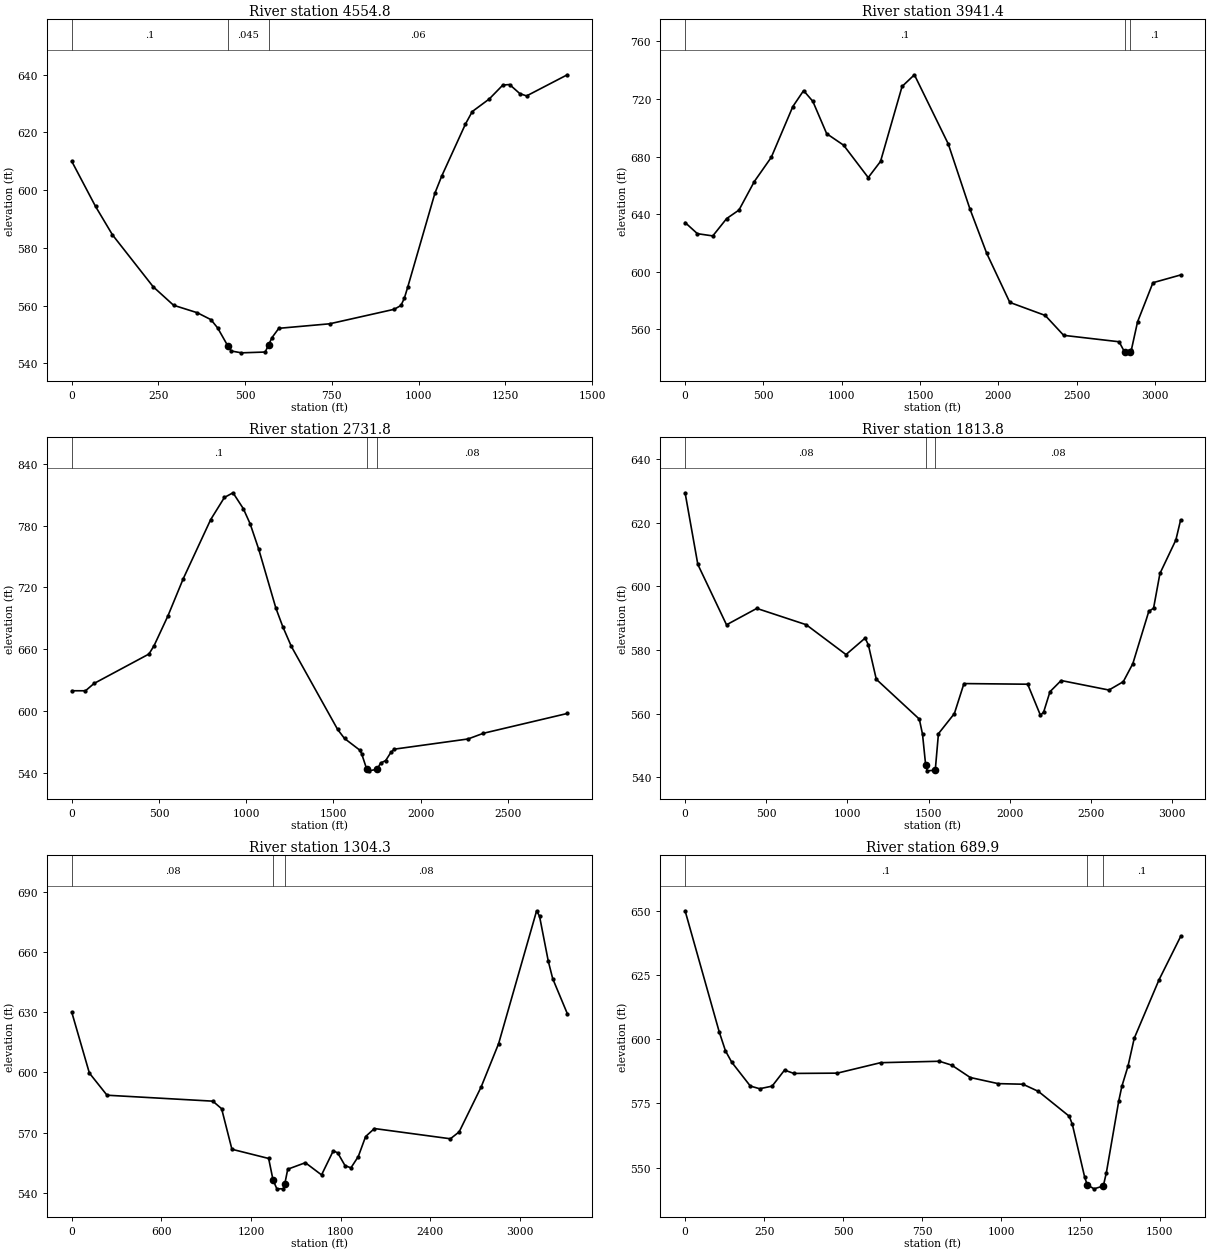
Type RM Length L Ch R = 1 ,4554.8  ,616.3,613.3,608.8
XS GIS Cut Line= 2
     1698714.781      589608.755     1699436.009      590841.905
#Sta/Elev= 30
       0     610    68.5  594.37   117.4   584.5   234.8   566.5   293.5   560.1
     362   557.5   401.2  555.11   420.7  552.22   450.1  545.96   459.7  544.24
   489.2   543.6   557.7  543.88   567.5  546.37   577.3  548.89   596.9   552.1
   743.6  553.67   929.6   558.7   949.1  560.03   958.9  562.58   968.7  566.44
    1047  598.98  1066.5  604.86    1135  622.92  1154.6  627.25  1203.5   631.6
  1242.7  636.43  1262.2  636.62  1291.6  633.48  1311.2  632.67  1428.6     640
#Mann= 3 , 0 , 0
       0      .1       0   450.1    .045       0   567.5     .06       0
Bank Sta=450.1,567.5
XS Rating Curve= 0 ,0
Exp/Cntr=0.3,0.1

Type RM Length L Ch R = 1 ,3941.4  ,1234.7,1209.6,1184.4
XS GIS Cut Line= 2
     1698112.346      587782.823      1698827.56      590863.896
#Sta/Elev= 30
       0  634.16    78.6   626.4   176.8  624.85   265.2   636.9   343.8  642.81
     442  662.66   550.1  679.46   687.6  714.72   756.4  725.82   815.3  718.37
   903.7  695.89  1011.8  687.89  1168.9  665.39  1247.5  676.63    1385  728.71
  1463.6  736.82  1679.7  688.78  1817.2  643.86  1925.3  612.72  2072.6  578.65
  2298.6  569.59  2416.4  555.76  2770.1   551.3  2806.5  543.91  2809.4   543.6
  2838.8  543.92  2848.7  545.72    2888  565.13  2986.2  592.33    3163  597.72
#Mann= 3 , 0 , 0
       0      .1       0  2806.5    .045       0  2838.8      .1       0
Bank Sta=2806.5,2838.8
XS Rating Curve= 0 ,0
Exp/Cntr=0.3,0.1

Type RM Length L Ch R = 1 ,2731.8  ,925,918,911
XS GIS Cut Line= 3
     1696082.554      590290.529     1698394.443      590897.024
     1698845.638      590906.053
#Sta/Elev= 30
       0     620    78.7  619.98   127.9  627.07   442.6  655.56   472.1  663.71
   550.8  692.24   639.3  728.52   796.7  785.79   875.4  807.21   924.6  811.72
   983.6  796.38  1022.9  781.64  1072.1  757.04  1170.5  699.97  1209.8  682.14
    1259  662.98  1524.6   582.5  1563.9   573.8  1652.4  562.39  1662.3  558.96
  1691.8  543.82  1701.6  542.45  1750.8  543.91  1770.5   549.9    1800  552.42
  1829.5  560.22  1849.2  563.44  2272.1  573.31  2360.6  578.84  2841.4  598.01
#Mann= 3 , 0 , 0
       0      .1       0  1691.8    .045       0  1750.8     .08       0
Bank Sta=1691.8,1750.8
XS Rating Curve= 0 ,0
Exp/Cntr=0.3,0.1

Type RM Length L Ch R = 1 ,1813.8  ,510.7,509.5,508.4
XS GIS Cut Line= 2
     1696187.115      591687.303     1699236.074      591539.423
#Sta/Elev= 30
       0  629.34    78.5  606.83   255.2  587.87   441.7  593.02     746   587.9
   991.3  578.52  1109.1   583.7  1128.8  581.57  1177.8  570.76  1442.8  558.25
  1462.5  553.51  1482.1  543.69  1491.9     542    1541   542.2  1560.6  553.67
  1658.8  559.99  1717.7  569.41  2110.3  569.21  2188.8  559.46  2208.4  560.43
  2247.7  566.86  2316.4  570.37  2610.9  567.38  2699.2     570  2758.1  575.68
  2856.2  592.08  2885.7  593.08    2925  603.99  3023.1  614.51  3052.5  620.82
#Mann= 3 , 0 , 0
       0     .08       0  1482.1    .045       0    1541     .08       0
Bank Sta=1482.1,1541
XS Rating Curve= 0 ,0
Exp/Cntr=0.3,0.1

Type RM Length L Ch R = 1 ,1304.3  ,607,614.4,621.7
XS GIS Cut Line= 3
     1696375.604      592258.612     1698372.147      592055.828
     1699490.385      592740.171
#Sta/Elev= 30
       0     630     118  599.67   236.1  588.64   944.4  585.68  1003.4  581.91
  1072.3  561.72  1318.2  557.13  1347.7  546.38  1373.2     542  1416.6  542.02
  1426.4  544.53  1446.1  551.78  1564.1  555.02  1672.4  548.94    1751  560.95
  1780.6  559.92  1829.7  553.56  1869.1  552.46  1918.3  558.08  1967.5  568.06
  2026.4  572.04  2535.1  566.94  2593.8  570.38  2740.6  592.69    2858  614.35
  3112.4  680.52    3132  677.77  3190.6  655.37    3220  646.72  3317.8  629.29
#Mann= 3 , 0 , 0
       0     .08       0  1347.7    .045       0  1426.4     .08       0
Bank Sta=1347.7,1426.4
XS Rating Curve= 0 ,0
Exp/Cntr=0.3,0.1

Type RM Length L Ch R = 1 ,689.9   ,363,359,355
XS GIS Cut Line= 3
      1696634.26      592709.142     1697011.648      592519.155
     1698129.794      592762.205
#Sta/Elev= 30
       0     650   108.1  602.77   127.7  595.46   147.4  591.06   206.3  581.76
   235.8  580.72   275.1  581.73   314.4  587.97   343.9  586.68   481.2  586.79
   618.1  590.86   803.9  591.42     843   589.9   901.7  585.09   989.8  582.71
    1068  582.48  1116.9   579.7  1214.7     570  1224.5   566.8  1263.6  546.18
  1271.5  543.35  1292.9  541.75  1322.3  542.86    1332  548.06  1371.2     576
    1381  581.67  1400.5  589.57  1420.1  600.37  1498.3  623.09  1566.8     640
#Mann= 3 , 0 , 0
       0      .1       0  1271.5    .045       0  1322.3      .1       0
Bank Sta=1271.5,1322.3
XS Rating Curve= 0 ,0
Exp/Cntr=0.3,0.1

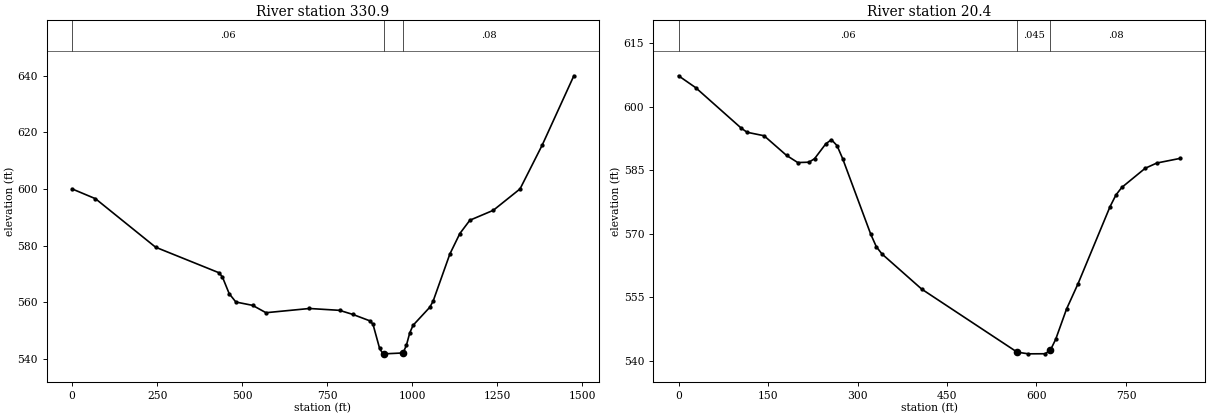
Type RM Length L Ch R = 1 ,330.9   ,311.8,310.4,309.1
XS GIS Cut Line= 3
     1696814.131      593007.649     1698129.794      593057.053
     1698231.056       592935.52
#Sta/Elev= 30
       0  600.01    68.8  596.54   245.6  579.39   432.3  570.34   442.1  568.81
   461.8  562.97   481.4  560.02   530.6  558.84   569.9  556.24   697.6  557.73
     786  557.08   825.3  555.63   874.4   553.4   884.3  552.21   903.9  543.61
   913.8   541.7     918   541.7   972.7  542.01   982.5  544.66   992.4  549.08
  1002.2  551.79  1051.3  558.16  1061.1  560.31  1110.3  576.97  1139.7  584.23
  1169.2  588.94    1238  592.44  1316.6     600  1381.7  615.48  1474.8     640
#Mann= 3 , 0 , 0
       0     .06       0     918    .045       0   972.7     .08       0
Bank Sta=918,972.7
XS Rating Curve= 0 ,0
Exp/Cntr=0.3,0.1

Type RM Length L Ch R = 1 ,20.4    ,16.8,20.4,24.1
XS GIS Cut Line= 6
     1697211.313      593624.898     1697298.492      593535.955
     1697476.968      593353.864     1697738.243      593347.826
     1697780.546      593339.315     1697925.881      593279.652
#Sta/Elev= 30
       0   607.3    28.7   604.5   105.4  594.91     115  593.97   143.4  593.15
     181  588.52   199.8  586.83   218.6  586.91     228  587.74   246.9  591.26
   256.3  592.22   265.7  590.82   275.1  587.75   322.1  569.95   331.6  566.95
   341.1  565.25   407.7  556.96   567.6   542.1   586.4   541.7   614.6  541.72
   623.4   542.6   632.1   545.1   650.4  552.28   669.6  558.23   723.3  576.43
   733.1  579.16   742.9  580.95   782.2  585.48   801.8  586.72   841.1  587.82
#Mann= 3 , 0 , 0
       0     .06       0   567.6    .045       0   623.4     .08       0
Bank Sta=567.6,623.4
XS Rating Curve= 0 ,0
Exp/Cntr=0.3,0.1

Chan Stop Cuts=-1
Use User Specified Reach Order=0
Composite Channel Slope=5